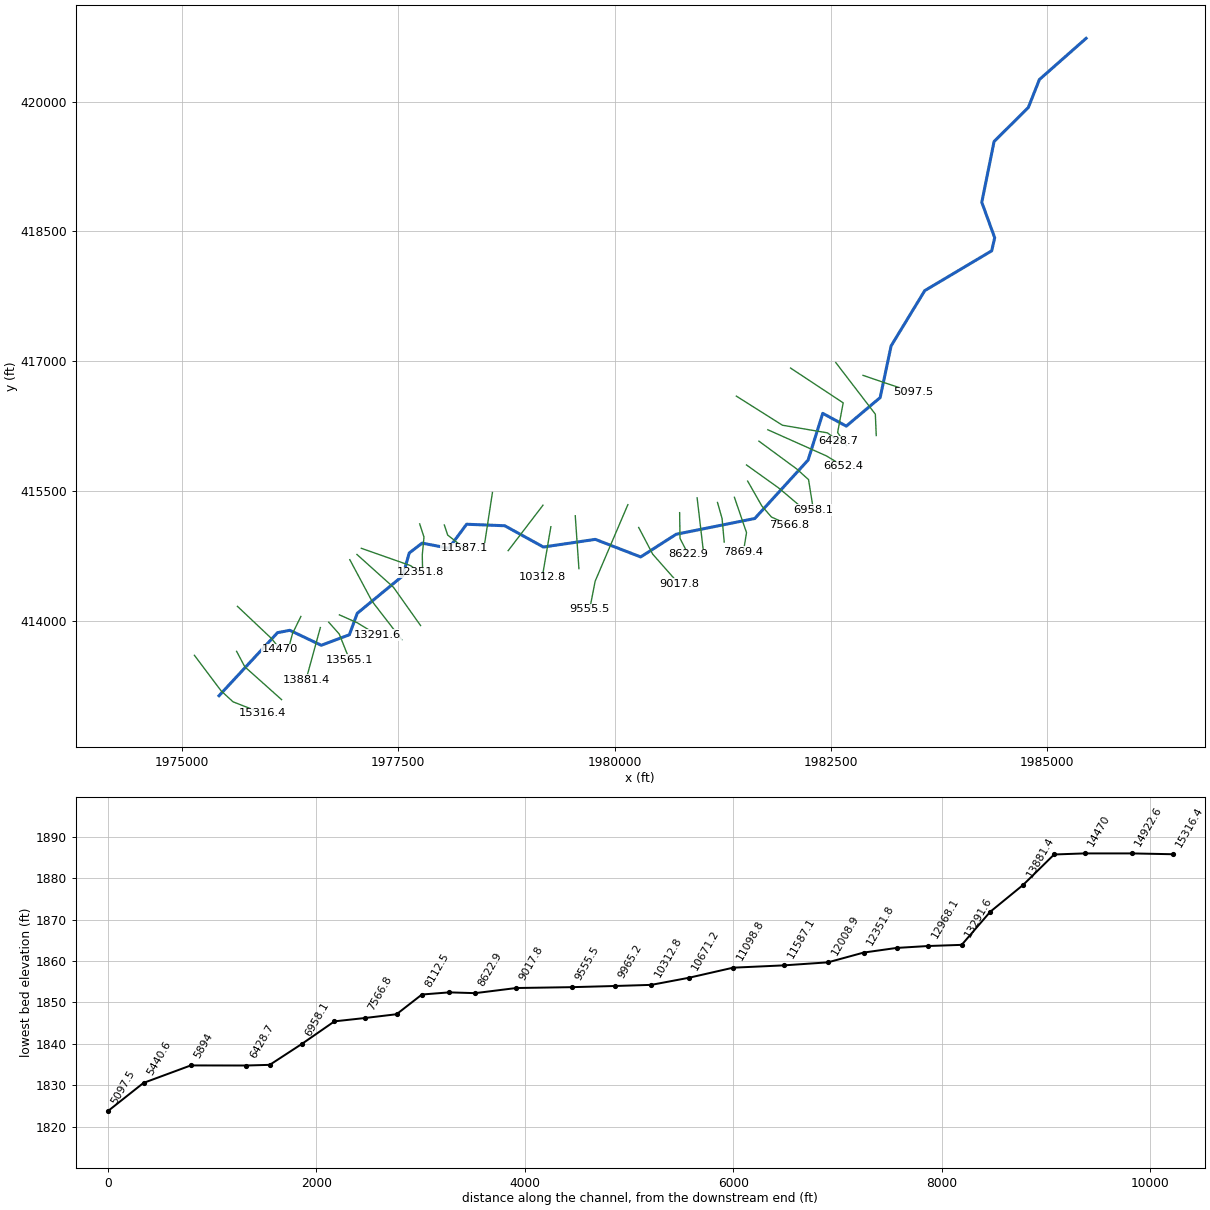
--- HedricksCk.prj (project) ---

Proj Title=HedricksCk
Current Plan=p01
Default Exp/Contr=0,0
English Units
Geom File=g01
Flow File=f01
Plan File=p01
BEGIN DESCRIPTION:
END DESCRIPTION:
DSS Export Rating Curves= 0
DSS Export Rating Curve Sorted= 0
DSS Export Volume Flow Curves= 0
DXF OffsetX= 0
DXF OffsetY= 0
DXF ScaleX= 0
DXF ScaleY= 0

--- HedricksCk.p01 (plan) ---

Plan Title=Floodplain
Program Version=4.00
Geom File=g01
Flow File=f01
K Sum by GR=0
Std Step Tol=0.01
Critical Tol=0.01
Num of Std Step Trials=20
Max Error Tol=0.3
Flow Tol Ratio=0.001
Split Flow NTrial=30
Split Flow Tol=0.02
Split Flow Ratio=0.02
Log Output Level=0
Friction Slope Method=1
Unsteady Friction Slope Method=2
Unsteady Bridges Friction Slope Method=1
Global Log Level=0
CheckData=False
Run HTab=0
Run UNet=0
Run PostProcess=0
UNET Theta=0
UNET Theta Warmup=0
UNET ZTol=0
UNET ZSATol=0
UNET MxIter=0
UNET MaxInSteps=0
UNET DtIC=0
UNET DtMin=0
UNET MaxCRTS=0
UNET WFStab=0
UNET SFStab=0
UNET WFX=0
UNET SFX=0
UNET DSS MLevel=0
UNET DZMax Abort=0
UNET Convert EG Bridges=0
UNET Use Existing IB Tables=0
UNET Froude Limit=0
UNET Froude Power=0
Write IC File=0
Echo Input=False
Echo Output=False
Write Detailed=0

--- HedricksCk.f01 (steady flow) ---

Flow Title=NFF Regression Equation
Program Version=4.00
Number of Profiles=1
Profile Names=P100yr
River Rch & RM=HedricksCk,Main      ,15316.4
552.7746
River Rch & RM=HedricksCk,Main      ,15316.4
552.7746
River Rch & RM=HedricksCk,Main      ,14922.6
618.2697
River Rch & RM=HedricksCk,Main      ,13565.1
643.5794
River Rch & RM=HedricksCk,Main      ,12008.9
714.8803
River Rch & RM=HedricksCk,Main      ,10312.8
777.5018
River Rch & RM=HedricksCk,Main      ,8374.9
857.8199
River Rch & RM=HedricksCk,Main      ,4032.5
950.9617
River Rch & RM=HedricksCk,Main      ,303.1
1051.254
Boundary for River Rch & Prof#=HedricksCk,Main      ,1
Up Type=0
Dn Type=3
Dn Slope=0.07728

--- HedricksCk.g01 (geometry) ---

Geom Title=USGS 3m DEM
Program Version=4.10

River Reach=HedricksCk      ,Main
Reach XY= 30
     1975425.961      413134.063     1976103.045       413863.23
     1976244.773      413890.257     1976608.253      413717.397
     1976932.906       413838.23      1977024.92      414087.188
     1977550.961       414519.48     1977625.726      414784.013
      1977774.92      414897.952     1978084.011      414838.837
     1978289.159      415116.169     1978730.611      415098.813
     1979177.698      414852.813     1979777.648      414941.355
     1980302.408       414738.23      1980712.42      415000.383
     1981622.142      415182.674     1982238.462      415858.022
     1982407.868      416397.675     1982680.217      416250.222
     1983071.795      416580.244     1983198.531      417177.466
     1983587.426      417816.132     1984361.725      418276.424
     1984396.447      418427.466     1984247.142      418837.188
     1984389.503      419540.313     1984785.336      419932.674
     1984913.137      420255.739     1985453.652      420732.296

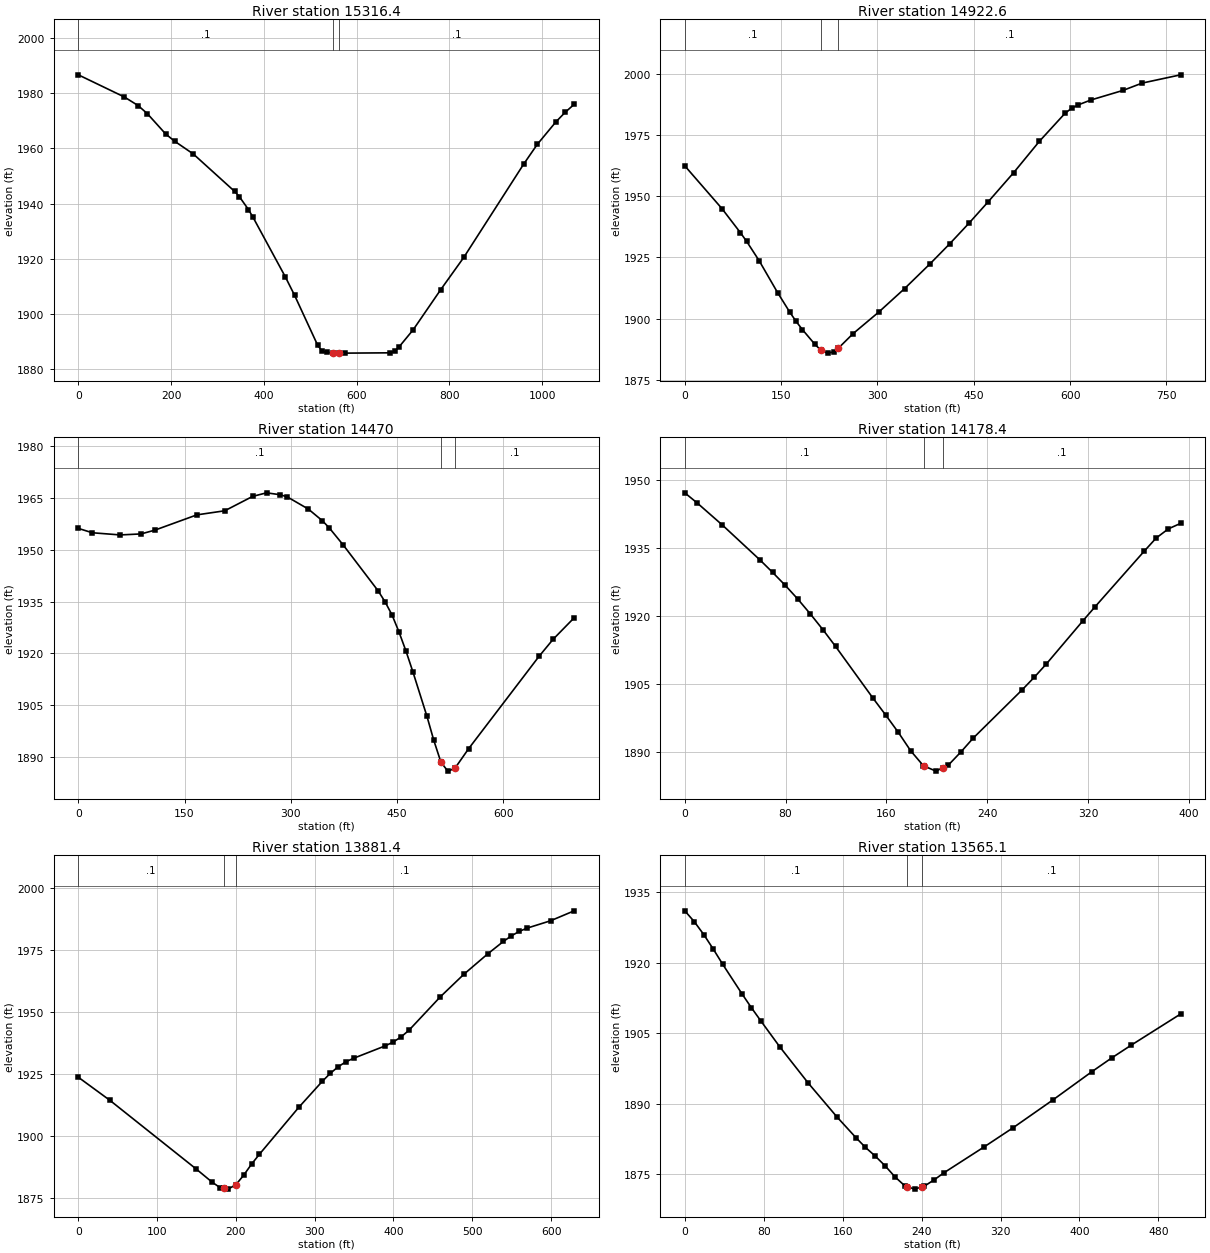
Type RM Length L Ch R = 1 ,15316.4 ,393.8,393.8,393.9
XS GIS Cut Line= 4
     1975141.316      413601.735     1975451.179        413189.7
     1975588.403      413063.705     1975930.213      412930.224
#Sta/Elev= 30
       0 1986.63    99.1 1978.61   128.9 1975.49   148.7 1972.57   188.4 1965.17
   208.2  1962.5   247.9 1957.94   337.1 1944.36     347 1942.51   366.8 1937.79
   376.8 1934.94   446.2 1913.43     466 1906.79   515.6 1888.76   525.4  1886.5
   535.2 1886.02   547.9 1885.99   562.9 1885.85   574.4 1885.79   672.4  1885.9
   682.2 1886.54     692 1888.18   721.7 1894.23   781.2  1908.8   830.8 1920.46
   959.7 1954.21   989.4 1961.45  1029.1 1969.51    1049 1972.98  1068.8 1975.94
#Mann= 3 , 0 , 0
       0      .1       0   547.9    .045       0   562.9      .1       0
Bank Sta=547.9,562.9
XS Rating Curve= 0 ,0
Exp/Cntr=0.3,0.1

Type RM Length L Ch R = 1 ,14922.6 ,453.2,452.6,450.8
XS GIS Cut Line= 3
     1975629.504      413647.231     1975724.301      413468.605
     1976149.509      413089.264
#Sta/Elev= 30
       0 1962.37    57.8 1944.95    86.7 1935.08    96.3 1931.56   115.6 1923.76
   144.4 1910.71   163.7  1902.6   173.3 1898.93     183 1895.62   202.2 1889.69
   212.2 1887.09   222.2 1885.99   232.2 1886.51   238.7 1887.91   262.2 1893.98
   302.2 1902.78   342.2 1912.31   382.2 1922.51   412.2 1930.51   442.2  1938.9
   472.1 1947.64   512.1 1959.62   552.1 1972.39   592.1 1983.83   602.1 1985.82
   612.1 1987.19   632.1 1989.22   682.1 1993.13   712.1 1996.13     772  1999.5
#Mann= 3 , 0 , 0
       0      .1       0   212.2    .045       0   238.7      .1       0
Bank Sta=212.2,238.7
XS Rating Curve= 0 ,0
Exp/Cntr=0.3,0.1

Type RM Length L Ch R = 1 ,14470   ,320.3,291.6,264.2
XS GIS Cut Line= 3
      1975639.19      414167.377     1976032.929      413795.598
     1976132.952      413672.237
#Sta/Elev= 30
       0 1956.15    19.7 1954.89    59.1 1954.26    88.6 1954.55   108.3 1955.66
   167.4 1960.06   206.8 1961.24   246.2  1965.4   265.8 1966.43   285.5 1965.87
   295.4 1965.22   324.9 1961.73   344.6 1958.38   354.4  1956.3   374.1 1951.36
   423.4 1938.11   433.2 1934.94   443.1 1931.12   452.9 1926.21   462.8 1920.67
   472.6 1914.65   492.3 1901.89   502.1 1894.86     512 1888.64   521.8 1885.99
   531.7 1886.75   551.4 1892.52   650.7 1919.17   670.6  1924.1   700.3 1930.31
#Mann= 3 , 0 , 0
       0      .1       0     512    .045       0   531.7      .1       0
Bank Sta=512,531.7
XS Rating Curve= 0 ,0
Exp/Cntr=0.3,0.1

Type RM Length L Ch R = 1 ,14178.4 ,292.7,296.9,301
XS GIS Cut Line= 3
     1976373.006      414050.656     1976276.318      413853.945
     1976231.307      413685.573
#Sta/Elev= 30
       0 1947.24      10 1944.96    29.9  1940.1    59.8 1932.37    69.7 1929.65
    79.7  1926.8    89.7 1923.75    99.6 1920.48   109.6    1917   119.6 1913.31
   149.4 1901.84   159.4 1898.14   169.4 1894.32   179.3 1890.21   189.3 1886.94
   189.6  1886.9   199.3 1885.73   204.6 1886.45   209.2 1887.07   219.2 1889.99
   228.9 1893.03   267.6 1903.66   277.3 1906.46     287 1909.44     316 1918.97
   325.7 1922.09   364.4 1934.28   374.1 1937.25   383.8 1939.28   393.5 1940.49
#Mann= 3 , 0 , 0
       0      .1       0   189.6    .045       0   204.6      .1       0
Bank Sta=189.6,204.6
XS Rating Curve= 0 ,0
Exp/Cntr=0.3,0.1

Type RM Length L Ch R = 1 ,13881.4 ,301.5,316.2,330.9
XS GIS Cut Line= 2
     1976598.057      413922.294     1976431.353      413315.489
#Sta/Elev= 30
       0 1923.55      40 1914.25   149.8 1886.46   169.8  1881.2   179.8 1879.02
   184.8  1878.7   189.8 1878.39   199.8  1880.1   209.8 1883.98   219.8 1888.46
   229.7 1892.41   279.7 1911.37   309.6 1921.89   319.6 1925.07   329.6 1927.74
   339.6  1929.8   349.6 1931.24   389.6 1936.23   399.6 1937.76   409.5  1939.8
   419.5 1942.47   459.5 1956.04   489.4 1965.14   519.4  1973.3   539.4 1978.35
   549.4 1980.58   559.4  1982.4   569.4 1983.73   599.3 1986.71   629.3 1990.73
#Mann= 3 , 0 , 0
       0      .1       0   184.8    .045       0   199.8      .1       0
Bank Sta=184.8,199.8
XS Rating Curve= 0 ,0
Exp/Cntr=0.3,0.1

Type RM Length L Ch R = 1 ,13565.1 ,255.8,273.4,290.9
XS GIS Cut Line= 3
     1976694.746      413983.974      1976816.44      413847.277
     1976934.801      413550.543
#Sta/Elev= 30
       0    1931     9.6  1928.7    19.3 1925.94    28.9 1922.86    38.5 1919.62
    57.8 1913.42    67.4 1910.45    77.1 1907.61    96.3  1902.1   125.2 1894.39
   154.1 1887.25   173.4 1882.83     183 1880.77     193 1878.91     203 1876.84
     213  1874.5     223 1872.58   225.6  1872.4   232.9 1871.89   240.6 1872.39
   242.9 1872.54   252.9 1873.89   262.9  1875.4   302.8 1880.78   332.8 1884.94
   372.7 1890.78   412.6 1896.84   432.6 1899.75   452.6 1902.49   502.5 1909.09
#Mann= 3 , 0 , 0
       0      .1       0   225.6    .045       0   240.6      .1       0
Bank Sta=225.6,240.6
XS Rating Curve= 0 ,0
Exp/Cntr=0.3,0.1

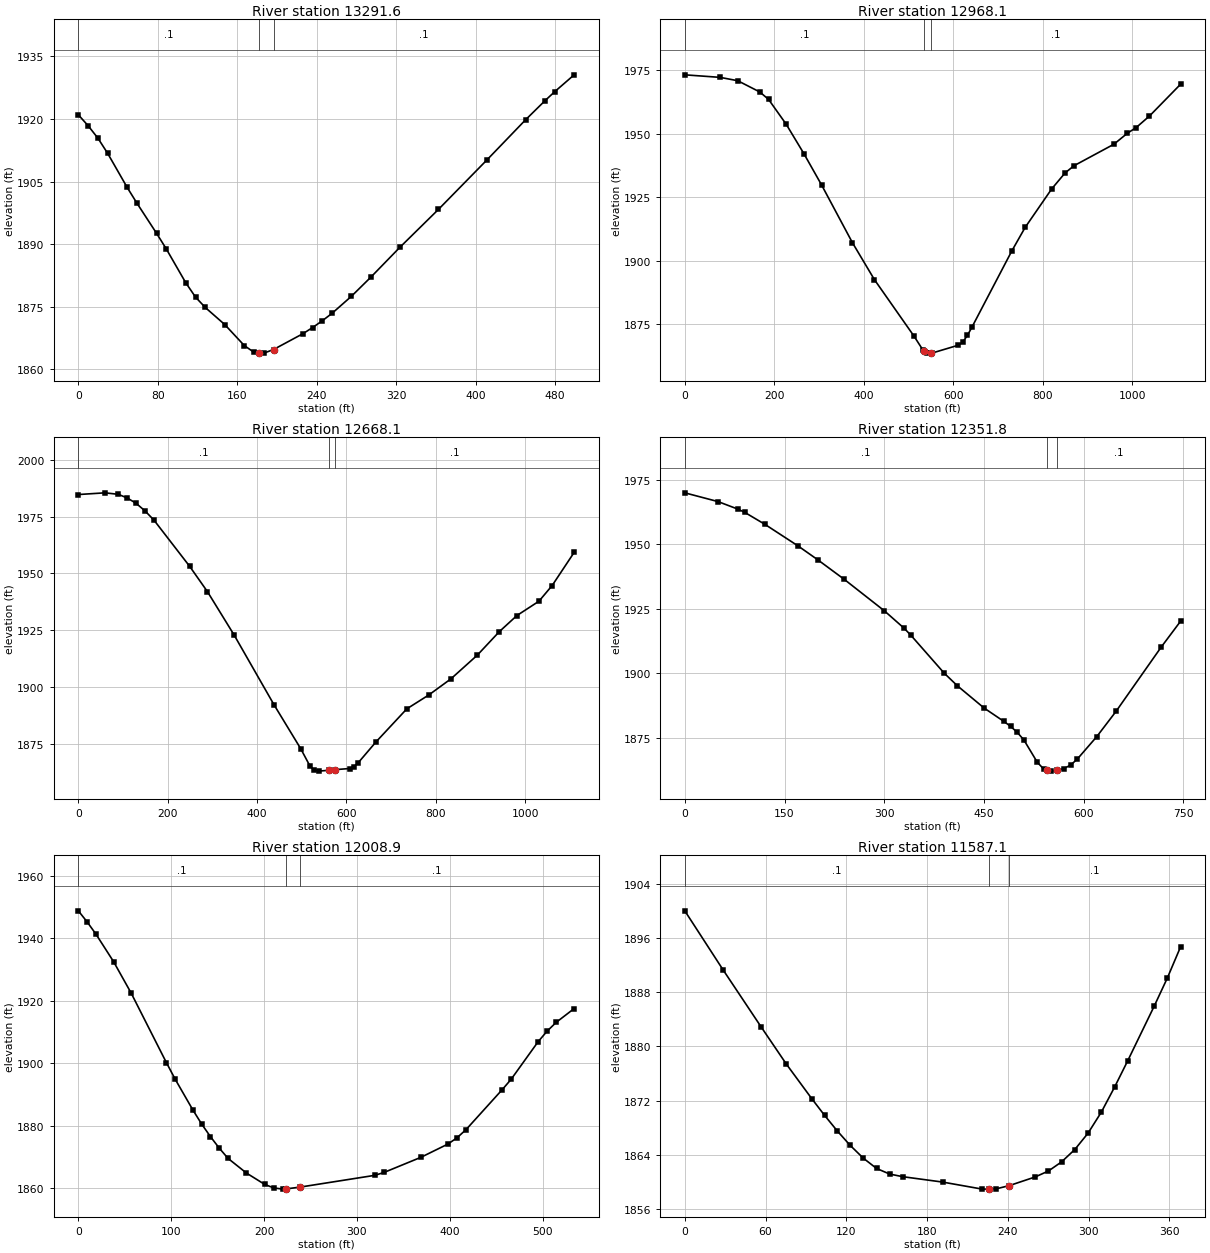
Type RM Length L Ch R = 1 ,13291.6 ,338.6,323.7,312.7
XS GIS Cut Line= 3
     1976818.107      414068.994     1977024.821      413977.306
     1977258.208      413835.607
#Sta/Elev= 30
       0 1920.97     9.8 1918.37    19.7 1915.38    29.5 1911.75    49.2 1903.57
      59 1899.81    78.7 1892.62    88.5 1888.88   108.2 1880.74     118 1877.32
   127.8 1874.84   147.5 1870.73   167.1 1865.72     177 1864.08   181.5    1864
   186.8 1863.91   196.5 1864.77   226.1 1868.56   235.9 1870.04   245.6 1871.65
   255.4 1873.43   274.9 1877.51   294.4 1882.07   323.6 1889.21   362.6 1898.33
   411.4 1910.17   450.4  1919.8   469.9 1924.36   479.7 1926.52   499.2 1930.54
#Mann= 3 , 0 , 0
       0      .1       0   181.5    .045       0   196.5      .1       0
Bank Sta=181.5,196.5
XS Rating Curve= 0 ,0
Exp/Cntr=0.3,0.1

Type RM Length L Ch R = 1 ,12968.1 ,292,299.9,298.8
XS GIS Cut Line= 3
     1976938.644      414706.719      1977194.23      414228.551
     1977540.173       413780.63
#Sta/Elev= 30
       0 1973.23    78.9 1972.23   118.3 1970.91   167.6 1966.48   187.3 1963.54
   226.7 1953.75   266.2 1942.18   305.6  1929.9   374.6 1907.14   423.9 1892.55
   512.6 1870.24   532.3 1864.83   534.7 1864.56   542.2  1863.7   549.7 1863.65
   552.1 1863.63   611.7 1866.77   621.6 1868.08   631.6 1870.59   641.5 1873.76
   730.8 1903.84   760.6 1913.11   820.2 1928.34     850  1934.6   869.8 1937.42
   959.2 1945.91     989  1950.2  1008.9 1952.47  1038.6 1957.01  1108.2 1969.54
#Mann= 3 , 0 , 0
       0      .1       0   534.7    .045       0   549.7      .1       0
Bank Sta=534.7,549.7
XS Rating Curve= 0 ,0
Exp/Cntr=0.3,0.1

Type RM Length L Ch R = 1 ,12668.1 ,307.4,316.2,330
XS GIS Cut Line= 3
     1977021.287      414766.661     1977443.708      414387.374
     1977757.092      413944.953
#Sta/Elev= 30
       0 1984.68    59.8 1985.43    89.6 1984.77   109.6 1983.15   129.5  1980.8
   149.4 1977.46   169.3 1973.44     249 1953.19   288.8 1942.08   348.6 1923.01
   438.2 1892.27     498 1872.96   517.9 1865.63   527.9 1863.57   537.8 1863.17
   560.2 1863.53   575.2 1863.83   607.1 1864.31     617 1865.15   626.9 1866.94
   666.3    1876   735.3 1890.53   784.6 1896.64   833.9 1903.68     893  1914.1
   942.3 1924.43   981.7 1931.51    1031  1937.8  1060.6 1944.69  1109.9 1959.27
#Mann= 3 , 0 , 0
       0      .1       0   560.2    .045       0   575.2      .1       0
Bank Sta=560.2,575.2
XS Rating Curve= 0 ,0
Exp/Cntr=0.3,0.1

Type RM Length L Ch R = 1 ,12351.8 ,373.1,342.9,312.7
XS GIS Cut Line= 3
     1977071.913      414838.032     1977638.294      414639.124
     1977759.988      414559.105
#Sta/Elev= 30
       0 1969.94      50 1966.54      80 1963.61      90 1962.39   120.1 1957.79
   170.1  1949.4   200.1 1943.97   240.1 1936.35   300.2  1924.2   330.2 1917.38
   340.2  1914.7   390.2 1900.04   410.2  1895.1   450.2 1886.52   480.2 1881.29
   490.2 1879.39   500.2 1877.06   510.2  1874.1   530.3 1865.48   540.3 1862.74
     545 1862.42   550.3 1862.05     560 1862.31   570.3 1863.04   580.3 1864.39
   590.3 1866.67   619.7 1875.41   648.8 1885.24   716.8 1910.18   745.9 1920.19
#Mann= 3 , 0 , 0
       0      .1       0     545    .045       0     560      .1       0
Bank Sta=545,560
XS Rating Curve= 0 ,0
Exp/Cntr=0.3,0.1

Type RM Length L Ch R = 1 ,12008.9 ,398.9,421.4,444.2
XS GIS Cut Line= 4
     1977746.652        415120.9     1977796.349      414967.562
     1977776.659      414760.818     1977779.993       414595.78
#Sta/Elev= 30
       0 1948.71     9.5 1945.16      19 1941.24    37.9 1932.48    56.9 1922.39
    94.8 1900.17   104.3 1894.84   123.3 1885.03   132.8 1880.51   142.2  1876.5
   151.7 1872.82   161.2 1869.52     181 1864.84   200.8 1861.18   210.6 1860.06
   220.5 1859.69   223.6 1859.76   238.6 1860.33   319.4 1864.11   329.3 1865.04
   368.9 1869.87     398 1874.11   407.7  1876.1   417.4  1878.7   456.3 1891.47
     466 1894.81   495.1 1906.85   504.8 1910.23   514.5 1913.02   533.9 1917.45
#Mann= 3 , 0 , 0
       0      .1       0   223.6    .045       0   238.6      .1       0
Bank Sta=223.6,238.6
XS Rating Curve= 0 ,0
Exp/Cntr=0.3,0.1

Type RM Length L Ch R = 1 ,11587.1 ,511.5,487.9,464.1
XS GIS Cut Line= 3
     1978031.717      415107.563     1978070.544      414991.148
     1978263.436      414839.169
#Sta/Elev= 28
       0 1899.98    28.3 1891.32    56.6  1882.9    75.5 1877.37    94.4 1872.27
   103.8 1869.84   113.3 1867.53   122.7 1865.44   132.5 1863.54   142.4 1862.01
   152.2 1861.18     162 1860.79   191.5    1860     221 1858.96   225.9 1858.97
   230.8 1858.98   240.9 1859.47   260.2 1860.75   270.1 1861.63   279.9 1862.98
   289.7  1864.8   299.5  1867.2   309.4 1870.31   319.2 1873.98     329 1877.88
   348.6  1885.9   358.5 1890.11   368.3 1894.69
#Mann= 3 , 0 , 0
       0      .1       0   225.9    .045       0   240.9      .1       0
Bank Sta=225.9,240.9
XS Rating Curve= 0 ,0
Exp/Cntr=0.3,0.1

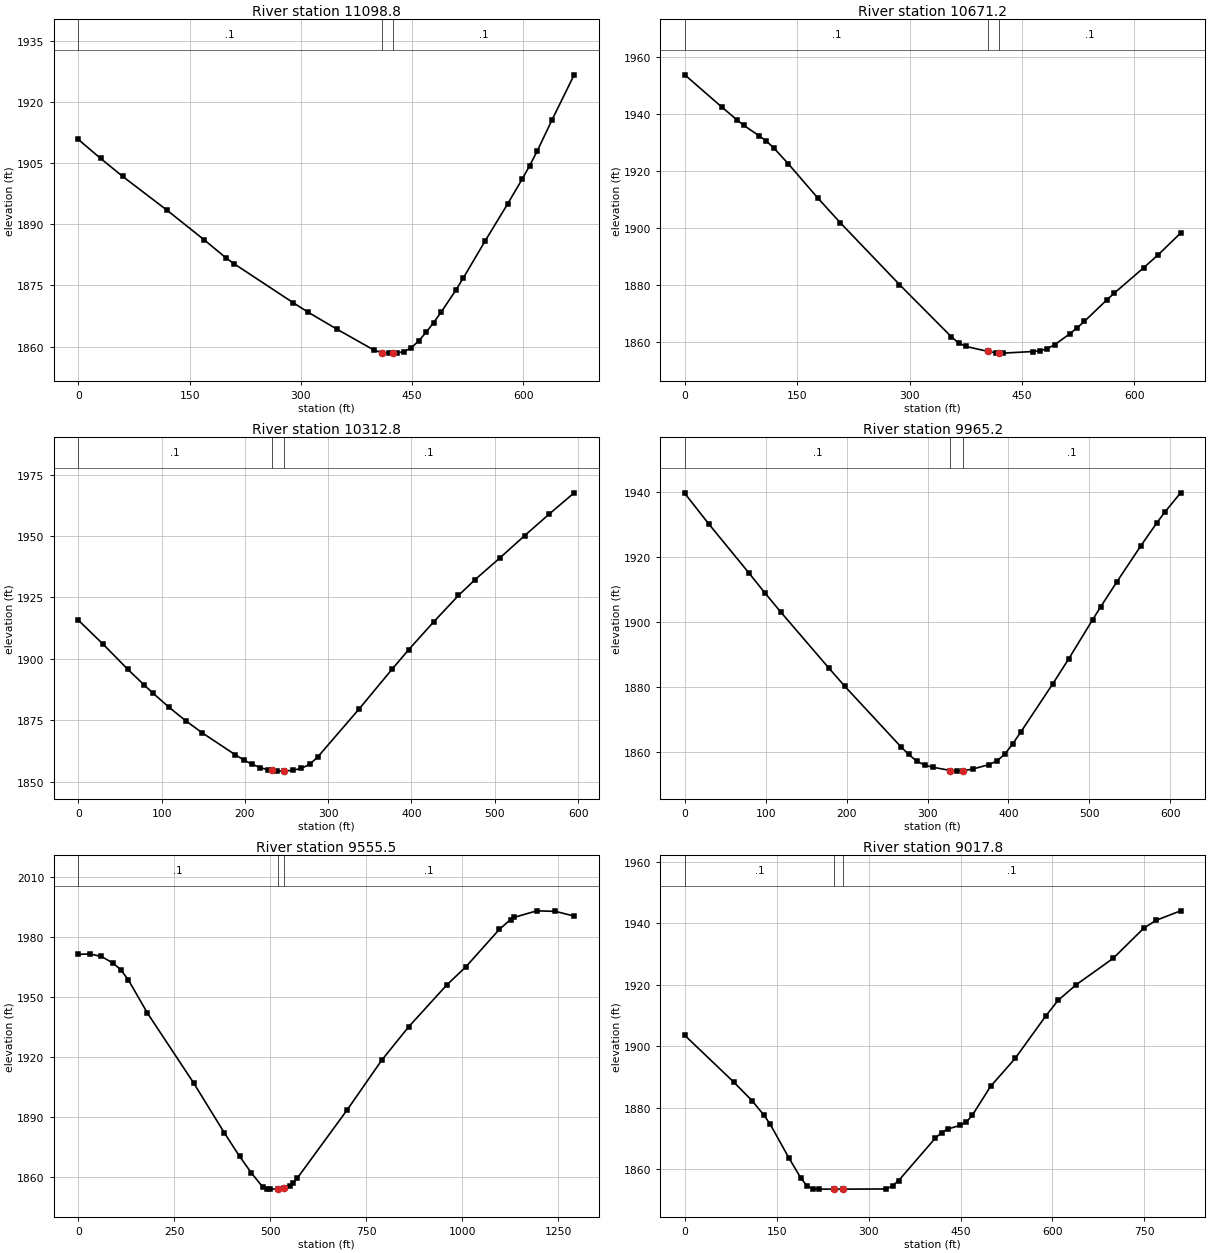
Type RM Length L Ch R = 1 ,11098.8 ,439.2,427,414.8
XS GIS Cut Line= 2
     1978588.094      415483.066     1978486.821      414822.499
#Sta/Elev= 30
       0  1910.8    29.9 1906.17    59.8 1901.74   119.7 1893.43   169.6 1886.19
   199.5 1881.69   209.5 1880.37   289.3  1870.8   309.2 1868.49   349.1 1864.22
     399 1859.09   409.4  1858.5   418.9  1858.4   424.4 1858.42   428.9 1858.44
   438.9 1858.75   448.8 1859.71   458.8  1861.4   468.8 1863.51   478.8 1865.87
   488.8  1868.4   508.7 1873.81   518.7 1876.77   548.6    1886   578.5 1894.96
   598.5 1901.16   608.4  1904.4   618.4 1907.93   638.4 1915.58   668.3 1926.66
#Mann= 3 , 0 , 0
       0      .1       0   409.4    .045       0   424.4      .1       0
Bank Sta=409.4,424.4
XS Rating Curve= 0 ,0
Exp/Cntr=0.3,0.1

Type RM Length L Ch R = 1 ,10671.2 ,347.7,358.3,369
XS GIS Cut Line= 2
     1979172.671      415336.366     1978770.218      414810.829
#Sta/Elev= 30
       0 1953.82    49.4 1942.48    69.2 1938.08      79    1936    98.8 1932.46
   108.7 1930.57   118.6 1928.16   138.3 1922.49   177.8 1910.42   207.5 1901.82
   286.5 1880.08   355.7 1861.74   365.6  1859.5   375.4  1858.3   404.9 1856.54
   414.9 1856.05   419.9    1856   424.8 1855.95   464.3 1856.51   474.2 1856.78
   484.1 1857.54     494 1858.96   513.7 1862.69   523.6 1864.82   533.5 1867.13
   563.1 1874.61     573 1876.98   612.5 1885.95   632.3 1890.63   661.9 1898.18
#Mann= 3 , 0 , 0
       0      .1       0   404.9    .045       0   419.9      .1       0
Bank Sta=404.9,419.9
XS Rating Curve= 0 ,0
Exp/Cntr=0.3,0.1

Type RM Length L Ch R = 1 ,10312.8 ,342.2,347.5,352.9
XS GIS Cut Line= 2
     1979263.664      415087.559     1979163.641      414500.759
#Sta/Elev= 30
       0 1915.69    29.8  1905.9    59.5 1895.65    79.4 1889.19    89.3 1886.08
   109.1 1880.19     129 1874.73   148.8 1869.83   188.5  1860.9   198.4 1858.84
   208.3 1857.08   218.3  1855.7   228.2 1854.72     232 1854.54   238.1 1854.25
     247 1854.26     258 1854.63   267.9  1855.4   277.8 1857.03   287.7 1860.11
   337.3 1879.64     377 1895.87   396.8 1903.75   426.6    1915   456.4 1925.76
   476.2 1932.17     506    1941   535.7 1950.07   565.5 1958.94   595.3 1967.54
#Mann= 3 , 0 , 0
       0      .1       0     232    .045       0     247      .1       0
Bank Sta=232,247
XS Rating Curve= 0 ,0
Exp/Cntr=0.3,0.1

Type RM Length L Ch R = 1 ,9965.2  ,420.2,409.4,398.6
XS GIS Cut Line= 2
      1979545.95      415214.532     1979588.182      414603.282
#Sta/Elev= 30
       0  1939.7    29.6 1930.28    79.1 1915.19    98.8 1909.04   118.6 1903.08
   177.9 1885.82   197.6  1880.2   266.8 1861.56   276.7 1859.12   286.6 1857.08
   296.5 1855.81   306.4 1855.19   328.3 1854.17     336 1853.98   343.3 1854.09
   355.8 1854.62   375.5 1855.97   385.4 1857.07   395.3  1859.2   405.2 1862.39
   415.1 1866.01   454.6 1880.88   474.4 1888.63     504 1900.74   513.9 1904.69
   533.6 1912.29   563.3 1923.44   583.1 1930.55   592.9 1933.84   612.7 1939.88
#Mann= 3 , 0 , 0
       0      .1       0   328.3    .045       0   343.3      .1       0
Bank Sta=328.3,343.3
XS Rating Curve= 0 ,0
Exp/Cntr=0.3,0.1

Type RM Length L Ch R = 1 ,9555.5  ,517.5,537.7,557.6
XS GIS Cut Line= 3
     1980154.226      415342.256     1979776.294      414459.156
     1979712.655      414134.286
#Sta/Elev= 30
       0 1971.23      30 1971.44      60 1970.19      90  1966.9   110.1 1963.63
   130.1 1958.51   180.1  1941.8   300.2 1906.89   380.2 1881.92   420.2 1870.08
   450.3 1861.93   480.3 1854.75   490.3 1853.79   500.3  1853.7   519.7 1853.77
   534.7 1854.31   550.3 1855.48   560.3  1856.9   570.3 1859.18   700.4 1893.39
   790.5 1918.29   860.5 1934.96   960.6 1956.08  1009.3 1964.94  1096.9 1983.77
  1126.1 1988.67  1135.8 1989.78  1194.2 1993.02  1242.9 1992.75  1291.6 1990.38
#Mann= 3 , 0 , 0
       0      .1       0   519.7    .045       0   534.7      .1       0
Bank Sta=519.7,534.7
XS Rating Curve= 0 ,0
Exp/Cntr=0.3,0.1

Type RM Length L Ch R = 1 ,9017.8  ,405.5,394.9,384.6
XS GIS Cut Line= 3
     1980279.451      415078.946      1980441.71      414769.987
     1980746.362      414425.047
#Sta/Elev= 30
       0 1903.54    79.8 1888.35   109.7 1882.29   129.6 1877.47   139.6 1874.53
   169.5 1863.78   189.4  1857.1   199.4 1854.53   209.4 1853.54   219.4 1853.49
     244 1853.49     259 1853.49     329 1853.54     339 1854.59     349 1856.28
     409 1870.13     419 1871.89     429 1873.04     449 1874.22     459 1875.26
     469 1877.46     499 1886.93   539.1 1896.03   589.1 1909.85   609.1 1914.92
   639.1 1920.07   699.1 1928.61   749.2 1938.46   769.2 1940.99   809.2 1944.08
#Mann= 3 , 0 , 0
       0      .1       0     244    .045       0     259      .1       0
Bank Sta=244,259
XS Rating Curve= 0 ,0
Exp/Cntr=0.3,0.1

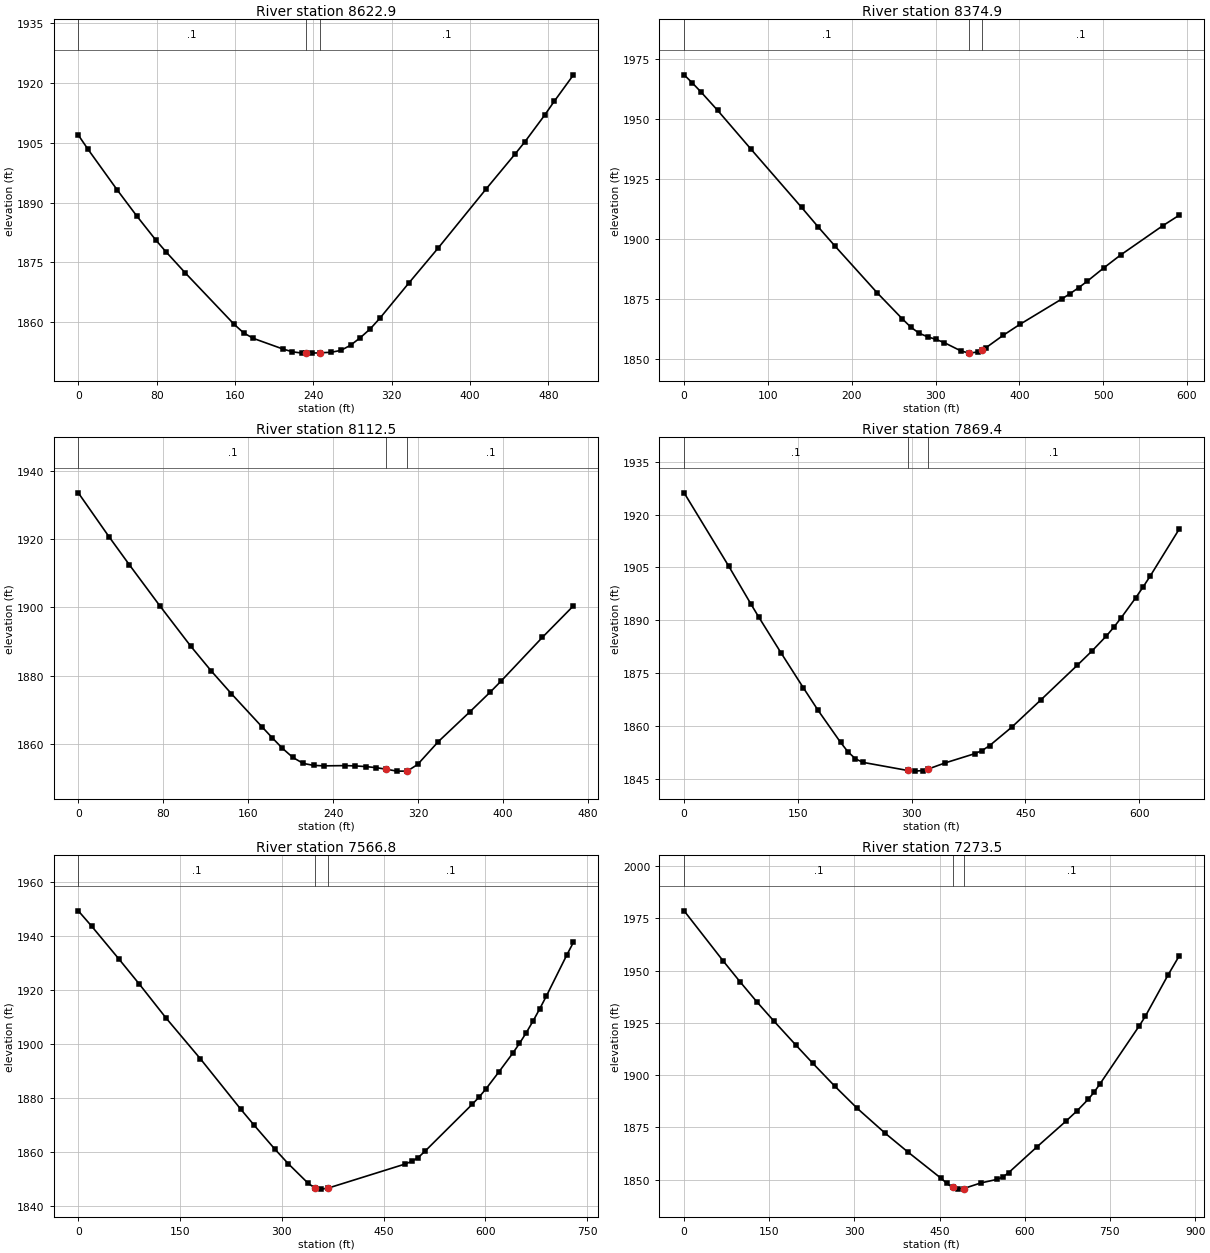
Type RM Length L Ch R = 1 ,8622.9  ,245.6,248,250.3
XS GIS Cut Line= 3
     1980752.892      415250.096     1980757.337       414952.25
     1980852.914      414767.764
#Sta/Elev= 30
       0 1906.96     9.9 1903.39    39.7  1893.2    59.6 1886.69    79.4 1880.54
    89.4 1877.71   109.2 1872.38   158.9 1859.53   168.8 1857.33   178.7 1855.95
   208.5 1853.32   218.4 1852.59   228.4 1852.26     232 1852.26   238.3 1852.25
     247 1852.34   258.2 1852.46   268.1 1852.94     278 1854.23     288 1856.14
   297.9 1858.29   307.8 1860.97   337.4 1869.81   367.1 1878.52   416.6  1893.5
   446.3  1902.3   456.2 1905.34     476  1911.9   485.9 1915.41   505.6 1922.07
#Mann= 3 , 0 , 0
       0      .1       0     232    .045       0     247      .1       0
Bank Sta=232,247
XS Rating Curve= 0 ,0
Exp/Cntr=0.3,0.1

Type RM Length L Ch R = 1 ,8374.9  ,262.9,262.3,261.6
XS GIS Cut Line= 2
      1980955.16      415421.246     1981024.064      414834.446
#Sta/Elev= 30
       0 1968.27      10 1964.83      20 1961.19    40.1 1953.44    80.1 1937.21
   140.2 1913.08   160.2 1904.87   180.2 1896.93   230.3 1877.57   260.4 1866.69
   270.4 1863.28   280.4 1860.73   290.4 1859.25   300.4 1858.17   310.4 1856.81
   330.5 1853.32   340.3 1852.44   350.5 1852.92   355.3 1853.81   360.5 1854.78
   380.5 1859.81   400.6 1864.41   450.6 1874.97   460.6 1877.23   470.7 1879.66
   480.7 1882.29   500.7 1887.91   520.7 1893.26   570.8  1905.4   590.8 1909.86
#Mann= 3 , 0 , 0
       0      .1       0   340.3    .045       0   355.3      .1       0
Bank Sta=340.3,355.3
XS Rating Curve= 0 ,0
Exp/Cntr=0.3,0.1

Type RM Length L Ch R = 1 ,8112.5  ,237.7,243.1,248.6
XS GIS Cut Line= 3
     1981190.769        415367.9      1981243.55      415182.955
     1981268.565      414910.019
#Sta/Elev= 28
       0 1933.66    28.8 1920.82    48.1 1912.52    76.9 1900.43   105.8 1888.66
     125 1881.42   144.2 1874.65   173.1  1864.9   182.7  1861.7   192.3 1858.61
   202.1 1855.93   211.9 1854.18   221.7  1853.6   231.5 1853.47   251.1 1853.54
   260.8 1853.46     271 1853.25   280.4 1852.94   290.2 1852.48     300 1851.92
   309.8 1851.92   319.6 1853.88   339.2 1860.62   368.5 1869.25   388.1 1875.17
   397.9 1878.27     437 1891.18   466.4 1900.49
#Mann= 3 , 0 , 0
       0      .1       0   290.2    .045       0   309.8      .1       0
Bank Sta=290.2,309.8
XS Rating Curve= 0 ,0
Exp/Cntr=0.3,0.1

Type RM Length L Ch R = 1 ,7869.4  ,294,302.7,311.3
XS GIS Cut Line= 3
     1981386.369      415427.914     1981526.401      415018.932
     1981490.837      414801.105
#Sta/Elev= 30
       0 1926.16      59 1905.29    88.4 1894.49    98.2 1890.98   127.7 1880.77
   157.2 1870.83   176.8 1864.38   206.3 1855.33   216.2 1852.61     226 1850.65
   235.8 1849.65   294.7 1847.35   304.6 1847.16   314.4 1847.32   321.4 1847.72
   343.9 1849.47   383.2 1852.11     393 1853.01   402.8 1854.39   432.3 1859.68
   470.7 1867.43   518.7 1877.26   537.8 1881.25     557 1885.56   566.6    1888
   576.2 1890.64   595.4 1896.32     605 1899.34   614.6 1902.52     653  1915.9
#Mann= 3 , 0 , 0
       0      .1       0   294.7    .045       0   321.4      .1       0
Bank Sta=294.7,321.4
XS Rating Curve= 0 ,0
Exp/Cntr=0.3,0.1

Type RM Length L Ch R = 1 ,7566.8  ,289.5,293.2,296.8
XS GIS Cut Line= 4
     1981539.737      415614.623      1981702.85      415328.632
     1981815.356      415198.973     1982024.292      415105.619
#Sta/Elev= 30
       0 1949.37      20 1943.58    59.9  1931.5    89.8 1922.26   129.7 1909.53
   179.6 1894.64   239.4 1875.87   259.4 1869.86   289.3 1861.18   309.3  1855.7
   338.8  1848.4   348.3 1846.76   357.8 1846.25   367.4 1846.57   481.8 1855.56
   491.4 1856.54   500.9 1857.94   510.8 1860.26   580.5 1877.67   590.4 1880.29
   600.4 1883.26   620.3 1889.83   640.2 1896.58   650.2 1900.24   660.1 1904.17
     670 1908.44     680 1913.04     690 1917.87   719.8 1932.93   729.8 1937.75
#Mann= 3 , 0 , 0
       0      .1       0   348.3    .045       0   367.4      .1       0
Bank Sta=348.3,367.4
XS Rating Curve= 0 ,0
Exp/Cntr=0.3,0.1

Type RM Length L Ch R = 1 ,7273.5  ,313.8,315,315.4
XS GIS Cut Line= 4
     1981526.401      415801.332     1981894.773      415537.875
     1981970.947      415474.591     1982215.447      415267.878
#Sta/Elev= 30
       0 1978.57    68.9 1954.57    98.4 1944.67     128 1935.08   157.5 1926.03
   196.9 1914.33   226.4 1905.72   265.8 1894.58   305.2 1884.02   354.4 1872.12
   393.8 1863.28   452.9 1850.55   462.8 1848.16   472.7 1846.26   482.6 1845.44
   492.5 1845.72   522.2 1848.37   551.9 1850.15   561.9 1851.33   571.9 1853.39
     622 1865.79     672 1877.83     692 1882.88     712 1888.49     722 1891.79
     732  1895.6     802 1923.69   812.1 1928.02   852.1 1947.78   872.1 1957.08
#Mann= 3 , 0 , 0
       0      .1       0   472.7    .045       0   492.5      .1       0
Bank Sta=472.7,492.5
XS Rating Curve= 0 ,0
Exp/Cntr=0.3,0.1

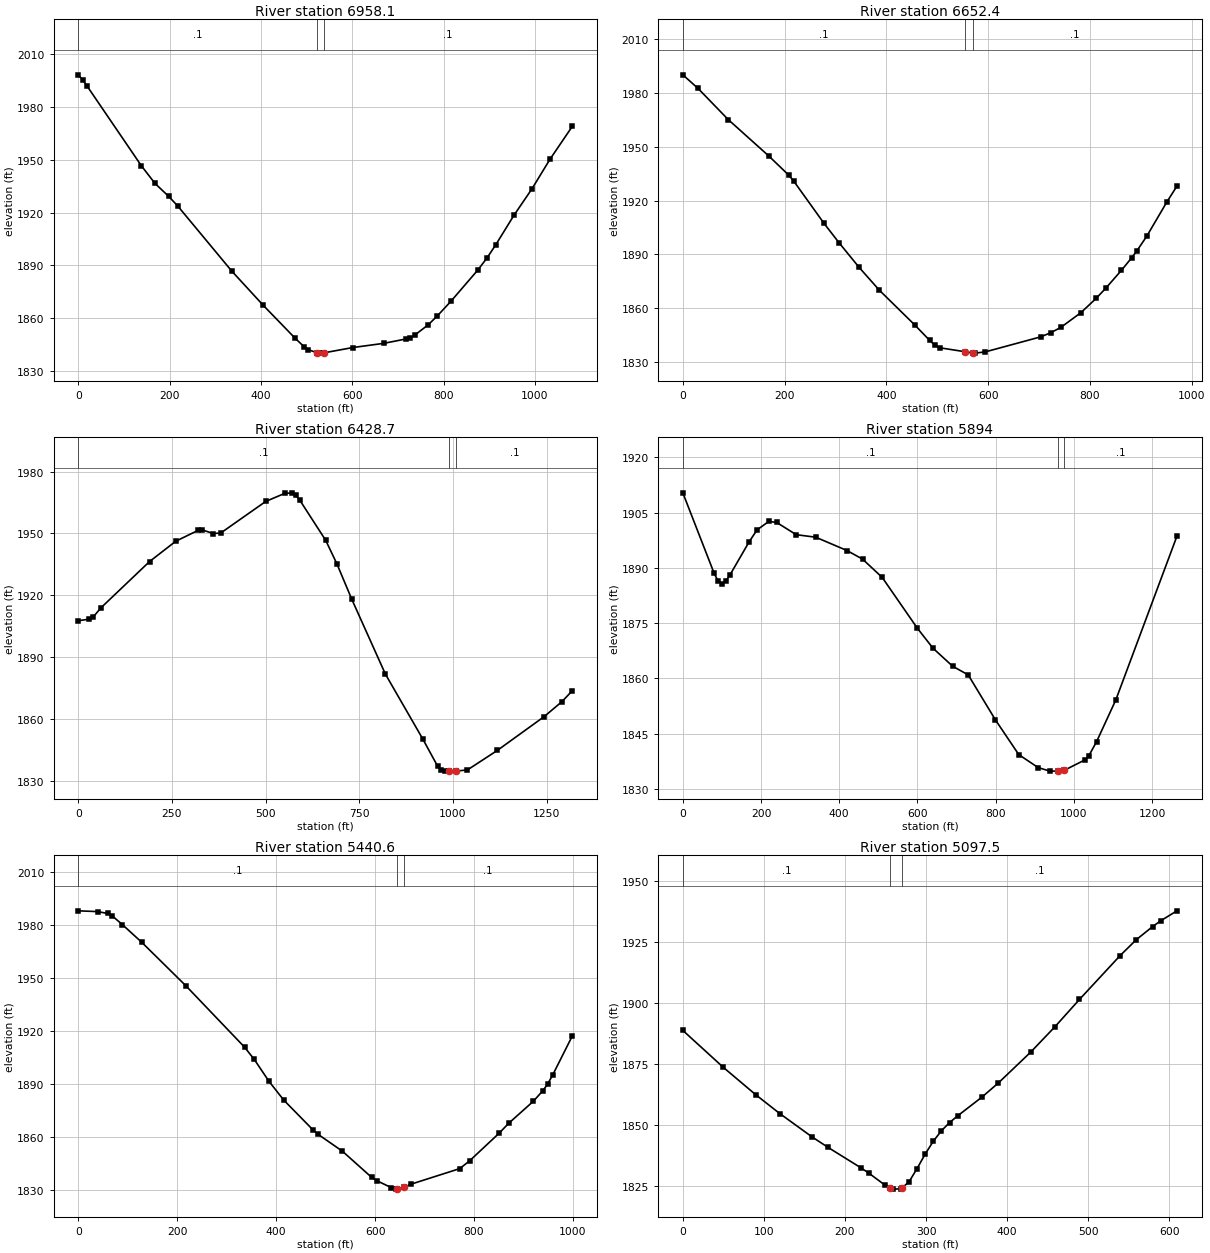
Type RM Length L Ch R = 1 ,6958.1  ,301,305.4,310.7
XS GIS Cut Line= 4
     1981669.604      416076.848     1982107.441      415754.666
     1982243.638      415631.867      1982299.91      415281.214
#Sta/Elev= 30
       0 1998.39     9.9 1995.44    19.8 1991.82   138.4 1946.55     168 1936.59
   197.7 1929.28   217.4 1923.86     336 1886.72   405.2 1867.15   474.4 1848.57
   494.2 1843.68   504.1 1841.88   522.5 1840.21   533.7 1839.95   537.5 1840.09
   601.5 1843.14   669.1 1845.52   717.3 1847.99     727 1848.67   736.8 1850.17
   766.4 1856.08   786.2 1861.08   815.8 1869.36     875 1887.24   894.7 1893.96
   914.4 1901.64   953.9 1918.31   993.3 1933.36  1032.8  1950.2  1082.1  1969.1
#Mann= 3 , 0 , 0
       0      .1       0   522.5    .045       0   537.5      .1       0
Bank Sta=522.5,537.5
XS Rating Curve= 0 ,0
Exp/Cntr=0.3,0.1

Type RM Length L Ch R = 1 ,6652.4  ,217.5,223.6,229.7
XS GIS Cut Line= 3
     1981772.672      416208.314     1982451.056      415905.801
     1982646.656      415787.996
#Sta/Elev= 30
       0 1990.06    29.7 1982.54    89.1 1965.15   168.4 1944.96     208 1934.19
   217.9 1930.86   277.3 1907.34     307 1896.47   346.6 1882.68   386.2 1870.02
   455.6  1850.7   485.3    1842   495.2 1839.37   505.1 1837.92   554.9 1835.71
   569.9 1835.07   574.4 1834.94   594.2 1835.62   703.2    1844     723  1846.3
   742.8 1849.26   782.5 1857.52   812.3 1865.46   832.1  1871.4   861.9 1881.06
   881.8 1887.98   891.7 1891.69   911.6 1900.02   951.3  1919.2   971.1 1928.04
#Mann= 3 , 0 , 0
       0      .1       0   554.9    .045       0   569.9      .1       0
Bank Sta=554.9,569.9
XS Rating Curve= 0 ,0
Exp/Cntr=0.3,0.1

Type RM Length L Ch R = 1 ,6428.7  ,547.5,533.8,482.3
XS GIS Cut Line= 4
     1981408.596      416597.069     1981941.915      416260.636
     1982462.169      416172.528     1982591.088      416076.951
#Sta/Elev= 30
       0 1907.68      30 1908.45      40 1909.49      60 1913.84   190.2 1936.35
   260.2  1946.2   320.3 1951.52   330.3 1951.73   360.3 1949.94   380.3 1950.19
   500.4  1965.5   550.5 1969.36   570.5 1969.67   580.5  1968.5   590.5 1966.33
   660.4 1946.65   690.3 1935.25   730.1 1918.05   819.7 1881.82   919.3 1850.42
   959.1 1837.17   969.1 1835.24     979 1834.78     989 1834.79  1008.9 1834.79
  1038.8 1835.38  1118.4 1844.81  1243.2 1861.17  1290.4 1868.38  1318.7 1873.76
#Mann= 3 , 0 , 0
       0      .1       0     989    .045       0  1008.9      .1       0
Bank Sta=989,1008.9
XS Rating Curve= 0 ,0
Exp/Cntr=0.3,0.1

Type RM Length L Ch R = 1 ,5894    ,457.2,453.4,464.1
XS GIS Cut Line= 4
     1982035.406      416921.587     1982644.433      416519.274
     1982579.974      416176.973     1982684.442      416023.605
#Sta/Elev= 30
       0 1910.34      80 1888.52      90 1886.42     100 1885.66     110 1886.42
     120 1887.95     170 1897.12     190  1900.3     220 1902.58     240  1902.3
     290 1898.98     340 1898.29     420 1894.67   459.9 1892.33   509.9 1887.38
   599.9 1873.58   639.9 1868.16   689.9 1863.29   729.9 1860.92   799.6  1848.7
   859.3 1839.28     909 1835.75   938.9  1834.8   960.4 1834.82   975.4 1835.01
  1028.5 1837.85  1038.4 1838.96  1058.3 1842.81  1107.5 1854.14  1263.8 1898.58
#Mann= 3 , 0 , 0
       0      .1       0   960.4    .045       0   975.4      .1       0
Bank Sta=960.4,975.4
XS Rating Curve= 0 ,0
Exp/Cntr=0.3,0.1

Type RM Length L Ch R = 1 ,5440.6  ,329.7,343.1,356.4
XS GIS Cut Line= 3
     1982558.663      416984.708     1983016.129      416388.594
     1983026.742       416141.41
#Sta/Elev= 30
       0 1988.06    39.6 1987.62    59.3 1986.57    69.2 1985.07      89 1980.31
   128.5 1970.22   217.5 1945.67   336.2  1910.9   355.9 1903.94   385.6 1891.56
   415.3    1881   474.6 1864.07   484.5 1861.65   533.9 1852.05   593.2 1837.21
   603.1 1835.41   632.8 1831.43   642.7 1830.58   643.7 1830.61   658.7 1831.68
   672.3 1833.35   771.2 1842.19     791 1846.57   850.4 1862.13   870.2 1867.86
   919.7 1880.24   939.4 1886.33   949.4 1890.33   959.2 1895.26   998.8 1917.32
#Mann= 3 , 0 , 0
       0      .1       0   643.7    .045       0   658.7      .1       0
Bank Sta=643.7,658.7
XS Rating Curve= 0 ,0
Exp/Cntr=0.3,0.1

Type RM Length L Ch R = 1 ,5097.5  ,231.3,232.6,233.9
XS GIS Cut Line= 3
     1982873.374      416837.124      1983146.77      416743.769
     1983451.283      416643.746
#Sta/Elev= 30
       0 1888.85    49.8 1873.74    89.7 1862.53   119.5 1854.76   159.4 1845.16
   179.3 1840.82   219.2 1832.58   229.1 1830.37     249 1825.46   255.7 1824.31
     259 1823.74     269 1823.87   270.7 1824.36   278.9  1826.7   288.9 1832.18
   298.9 1838.12   308.9 1843.38   318.9 1847.68     329 1851.05     339 1853.82
     369 1861.52   389.1 1867.28   429.1 1879.97   459.2 1890.45   489.2 1901.57
   539.3 1919.55   559.3 1926.08   579.4 1931.46   589.4 1933.84   609.4 1937.92
#Mann= 3 , 0 , 0
       0      .1       0   255.7    .045       0   270.7      .1       0
Bank Sta=255.7,270.7
XS Rating Curve= 0 ,0
Exp/Cntr=0.3,0.1