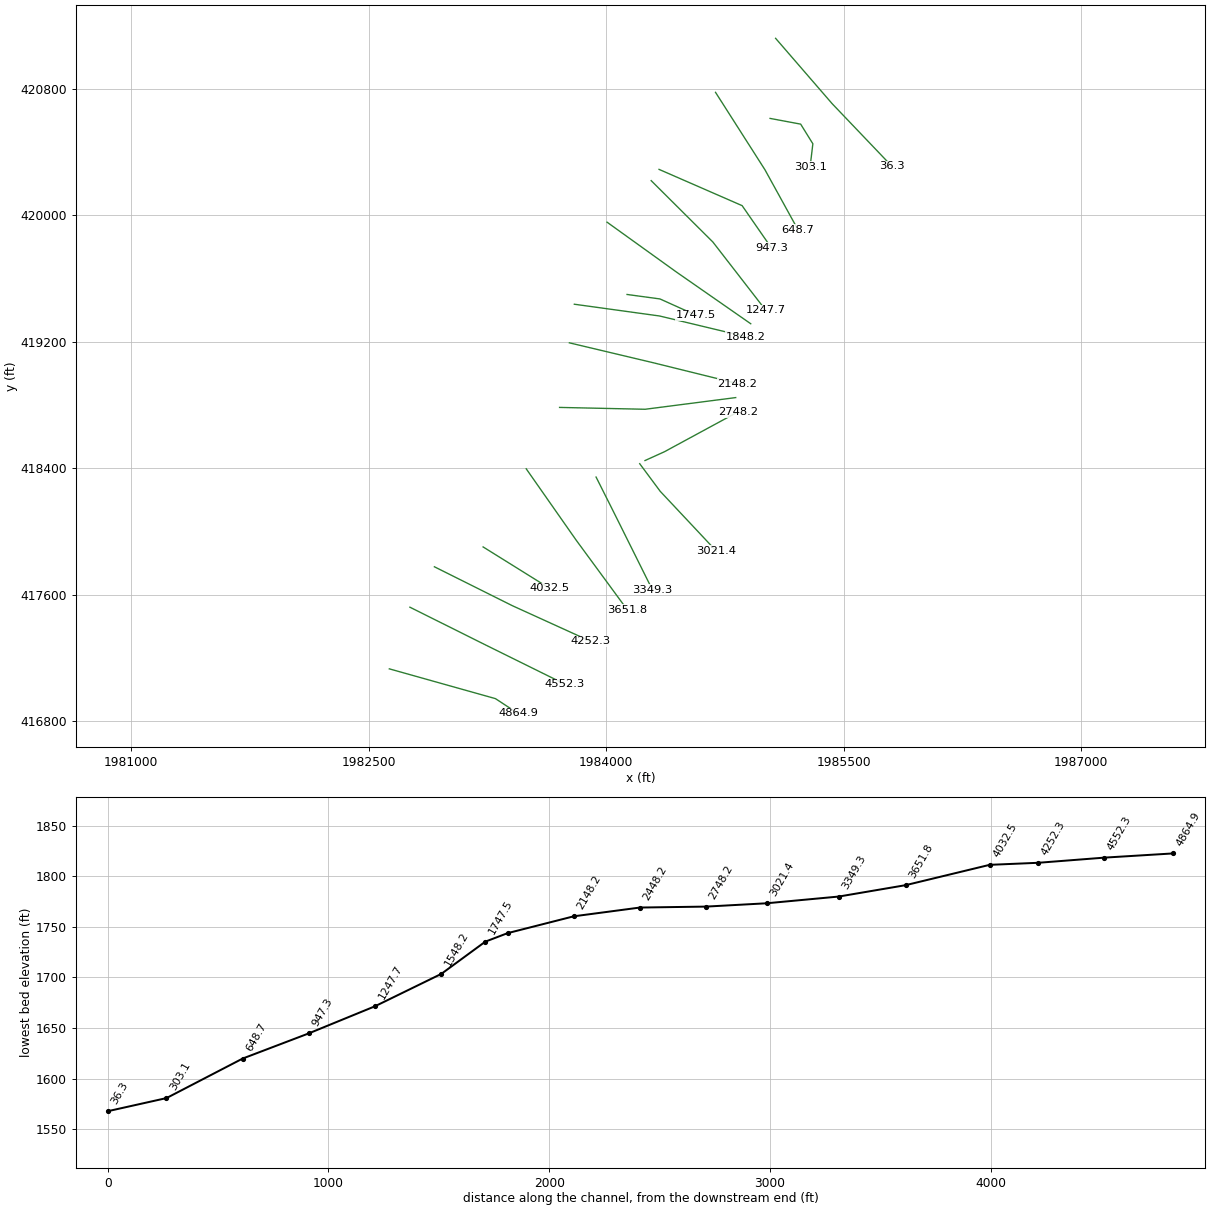
HEC-RAS study HedricksCk.prj: HedricksCk

--- HedricksCk.g01 (geometry) --- (continued)

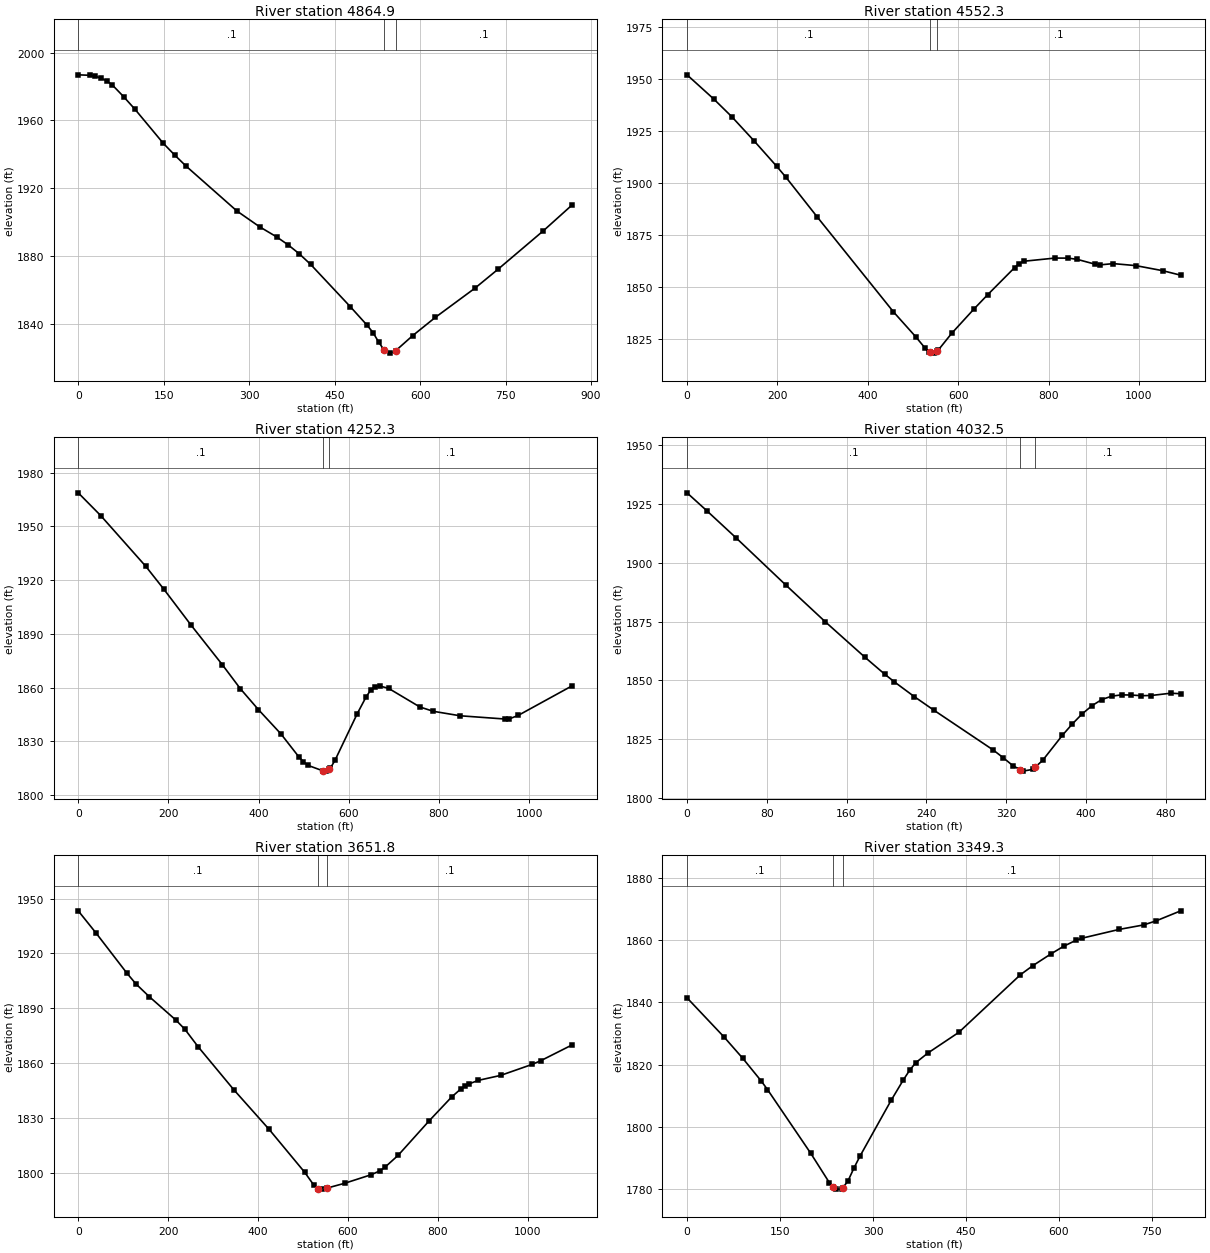
Type RM Length L Ch R = 1 ,4864.9  ,317,312.7,308.4
XS GIS Cut Line= 3
     1982629.793      417130.111     1983300.138      416941.592
     1983442.393      416848.237
#Sta/Elev= 30
       0  1986.9    19.9 1986.63    29.8 1986.08    39.8 1984.95    49.7 1983.37
    59.7 1980.96    79.6 1974.03    99.5  1966.6   149.2 1946.51   169.1  1939.6
     189 1933.09   278.5 1906.51   318.3 1897.19   348.2 1891.22   368.1  1886.6
     388 1881.23   407.9 1874.98   477.5 1850.03   507.3 1838.96   517.3 1834.76
   527.2 1829.21   537.2  1824.2   547.1  1822.6   557.1    1824   586.9  1832.9
   626.7 1843.68   696.4 1860.97   736.4 1872.01   816.5 1894.87   866.5 1909.98
#Mann= 3 , 0 , 0
       0      .1       0   537.2    .045       0   557.1      .1       0
Bank Sta=537.2,557.1
XS Rating Curve= 0 ,0
Exp/Cntr=0.3,0.1

Type RM Length L Ch R = 1 ,4552.3  ,299.9,299.9,300.7
XS GIS Cut Line= 3
     1982759.683      417520.415     1983247.941      417276.285
     1983737.803      417033.723
#Sta/Elev= 30
       0 1951.87    59.6 1940.18    99.2 1931.76   148.9 1920.08   198.5 1907.99
   218.4 1902.89   287.8 1883.81   456.6 1838.26   506.2 1826.25     526 1821.05
     536 1818.86   538.4 1818.76   545.9 1818.43   553.4 1819.51   555.8 1819.85
   585.6  1827.9   635.3 1839.66   665.2 1846.42   724.8 1859.41   734.7 1861.36
   744.7 1862.47   814.2 1864.01     844 1863.98   863.9 1863.36   903.7 1861.03
   913.6 1860.74   943.4 1861.35   993.1 1860.39  1052.8 1857.95  1092.5 1855.79
#Mann= 3 , 0 , 0
       0      .1       0   538.4    .045       0   553.4      .1       0
Bank Sta=538.4,553.4
XS Rating Curve= 0 ,0
Exp/Cntr=0.3,0.1

Type RM Length L Ch R = 1 ,4252.3  ,221.8,219.7,216.8
XS GIS Cut Line= 3
     1982914.453      417776.266     1983405.884      417530.353
     1983902.301      417303.886
#Sta/Elev= 30
       0 1968.69      50 1955.96   149.9 1927.65   189.8 1914.93   249.8    1895
   319.7 1872.72   359.7 1859.32   399.6  1847.7   449.6 1834.13   489.6 1821.23
   499.6 1818.58   509.6 1816.56     542 1813.56   549.5 1813.33     557 1814.63
   559.4 1815.05   569.4 1819.27     619 1845.43   638.8 1854.85   648.7 1858.51
   658.6 1860.46   668.6 1860.86   688.4 1859.55   757.9 1849.14   787.6 1846.73
   847.1 1844.23   946.4 1842.42   956.3  1842.5   976.1 1844.45  1095.2  1860.9
#Mann= 3 , 0 , 0
       0      .1       0     542    .045       0     557      .1       0
Bank Sta=542,557
XS Rating Curve= 0 ,0
Exp/Cntr=0.3,0.1

Type RM Length L Ch R = 1 ,4032.5  ,389.6,380.5,371.9
XS GIS Cut Line= 2
     1983222.342       417901.81     1983642.438      417639.528
#Sta/Elev= 30
       0 1929.84    19.8 1922.23    49.5 1910.54      99  1890.6   138.7 1874.91
   178.3 1859.87   198.1 1852.66     208 1849.32   227.8 1843.09   247.6 1837.26
     307 1820.34     317 1817.07   326.9 1813.62   334.3 1811.89   336.8 1811.31
   346.7 1812.04   349.3 1813.04   356.6 1815.84   376.4 1826.52   386.3 1831.32
   396.2 1835.64   406.1 1839.15     416  1841.8   425.9 1843.23   435.8 1843.79
   445.7 1843.72   455.6 1843.44   465.5 1843.52   485.3  1844.5   495.2 1844.27
#Mann= 3 , 0 , 0
       0      .1       0   334.3    .045       0   349.3      .1       0
Bank Sta=334.3,349.3
XS Rating Curve= 0 ,0
Exp/Cntr=0.3,0.1

Type RM Length L Ch R = 1 ,3651.8  ,305.7,302.5,298.6
XS GIS Cut Line= 3
     1983494.486      418396.425     1983811.198       417943.15
     1984133.387       417503.45
#Sta/Elev= 30
       0 1943.32    39.5 1931.22   108.6 1909.15   128.4 1903.37     158 1896.42
   217.2 1883.62     237 1878.66   266.6 1869.06   345.6 1845.67   424.6 1823.88
   503.6 1800.46   523.3 1793.68   533.2 1791.51   543.1 1791.23     553 1791.77
   592.6 1794.43   652.1 1799.14   671.9 1801.36   681.8  1803.1   711.5  1809.7
   780.9 1828.65   830.5 1841.57   850.3 1845.84   860.2 1847.43   870.1 1848.82
   889.9 1850.67   939.5 1853.38  1008.9 1859.34  1028.7  1861.4  1098.1    1870
#Mann= 3 , 0 , 0
       0      .1       0   533.2    .045       0     553      .1       0
Bank Sta=533.2,553
XS Rating Curve= 0 ,0
Exp/Cntr=0.3,0.1

Type RM Length L Ch R = 1 ,3349.3  ,323.8,327.7,334.2
XS GIS Cut Line= 3
     1983935.838      418344.133     1984047.827      418120.993
      1984291.07      417631.366
#Sta/Elev= 30
       0 1841.49    59.9 1828.86    89.9 1822.05   119.8 1814.73   129.8    1812
   199.7 1791.47   229.7 1782.04   235.9 1780.77   239.7 1779.99   249.7    1780
   250.9 1780.32   259.6  1782.6   269.6 1786.91   279.5 1790.77   329.2 1808.52
   349.1 1815.15     359 1818.17     369 1820.64   388.8 1823.78   438.5  1830.4
   537.9 1848.93   557.8 1851.83   587.6 1855.68   607.5 1858.06   627.4 1859.99
   637.3 1860.67     697 1863.48   736.7 1864.93   756.6 1866.23   796.4 1869.46
#Mann= 3 , 0 , 0
       0      .1       0   235.9    .045       0   250.9      .1       0
Bank Sta=235.9,250.9
XS Rating Curve= 0 ,0
Exp/Cntr=0.3,0.1

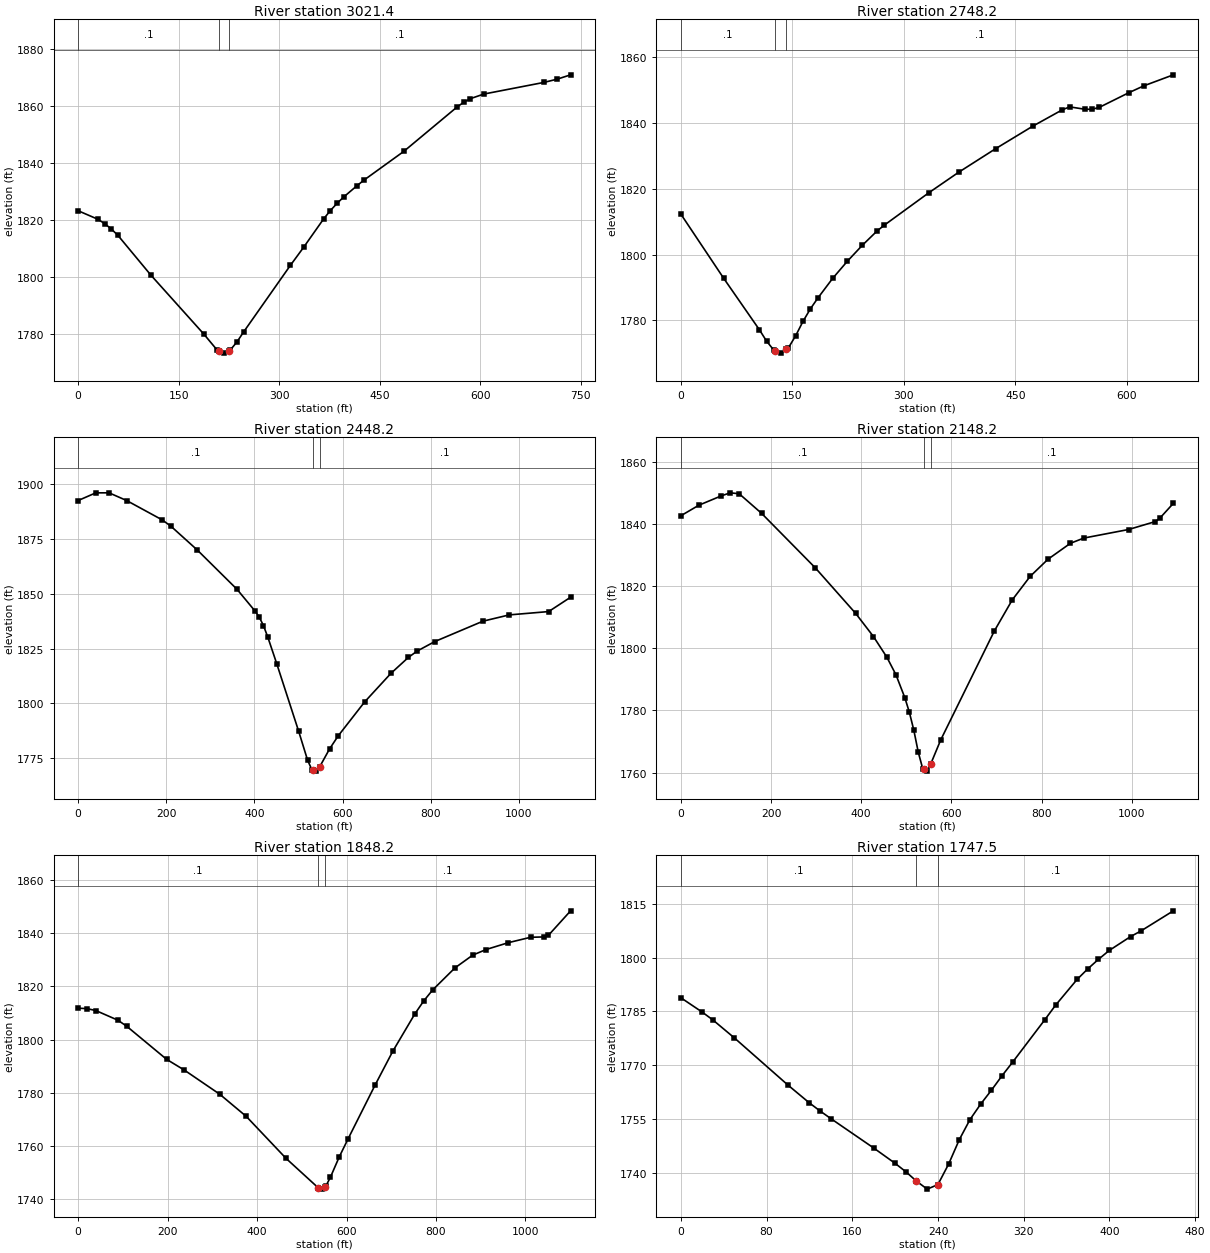
Type RM Length L Ch R = 1 ,3021.4  ,242.6,273.3,303.1
XS GIS Cut Line= 3
     1984211.456      418428.597     1984340.722      418254.271
     1984694.733      417876.297
#Sta/Elev= 30
       0 1823.23    29.6 1820.23    39.5 1818.71    49.3 1816.88    59.2 1814.63
   108.5 1800.67   187.4 1780.03   207.2 1774.45     210 1774.13     217 1773.32
     225 1774.19     227 1774.41   236.9 1777.22   246.9 1780.74   316.6 1804.05
   336.5 1810.43   366.4  1820.4   376.4  1823.3   386.3 1825.81   396.3 1828.06
   416.2 1832.03   426.2 1833.91   485.9 1844.03   565.6 1859.63   575.6 1861.29
   585.5 1862.54   605.4 1864.14   695.1 1868.22     715 1869.37   734.9 1870.88
#Mann= 3 , 0 , 0
       0      .1       0     210    .045       0     225      .1       0
Bank Sta=210,225
XS Rating Curve= 0 ,0
Exp/Cntr=0.3,0.1

Type RM Length L Ch R = 1 ,2748.2  ,310,299.9,291.6
XS GIS Cut Line= 3
     1984244.797      418448.601     1984367.136      418504.126
     1984831.187      418756.177
#Sta/Elev= 30
       0 1812.25    57.6 1792.76   105.6 1777.14   115.2 1773.71   124.8    1771
   126.8  1770.8   134.4 1770.05   141.8 1771.17   144.3 1771.55   154.3  1775.3
   164.2 1779.69   174.2 1783.51   184.2 1786.78   204.1 1792.75     224 1797.99
     244  1802.8   263.9 1807.16   273.8 1808.95   333.6 1818.78   373.5 1824.97
   423.3 1832.14   473.1 1838.96     513 1843.95   522.9 1844.85   542.9 1844.14
   552.8  1844.1   562.8  1844.7   602.6 1849.16   622.6 1851.23   662.4 1854.58
#Mann= 3 , 0 , 0
       0      .1       0   126.8    .045       0   141.8      .1       0
Bank Sta=126.8,141.8
XS Rating Curve= 0 ,0
Exp/Cntr=0.3,0.1

Type RM Length L Ch R = 1 ,2448.2  ,304.8,300,291.6
XS GIS Cut Line= 3
     1983705.312      418785.007     1984245.752       418773.26
     1984817.779      418847.183
#Sta/Elev= 30
       0 1892.64      40 1896.14    70.1 1896.15   110.1 1892.62   190.2 1883.85
   210.2 1880.96   270.3 1870.05   360.4 1852.12   400.4 1842.42   410.4 1839.61
   420.4 1835.57   430.4 1830.24   450.5 1818.21   500.5 1787.21   520.6 1774.11
   530.6 1769.64   533.1 1769.51   540.6 1769.12   548.1 1771.11   570.4 1779.24
   590.3 1785.29     650  1800.7   709.6 1813.73   749.4 1821.05   769.3 1823.93
   809.1 1828.25   918.5 1837.56   978.1 1840.43  1067.6 1841.95  1117.4  1848.5
#Mann= 3 , 0 , 0
       0      .1       0   533.1    .045       0   548.1      .1       0
Bank Sta=533.1,548.1
XS Rating Curve= 0 ,0
Exp/Cntr=0.3,0.1

Type RM Length L Ch R = 1 ,2148.2  ,297.6,299.8,299.9
XS GIS Cut Line= 3
     1983766.974      419193.843     1984298.548      419067.371
     1984828.512      418936.135
#Sta/Elev= 30
       0 1842.76    39.7 1846.14    89.4 1849.15   109.3 1850.14   129.2 1849.85
   178.8 1843.55     298 1825.98   387.5 1811.31   427.2 1803.81     457 1797.13
   476.9 1791.55   496.7 1784.13   506.7 1779.46   516.6 1773.69   526.5 1766.58
   536.5 1761.18   538.9    1761   546.4 1760.45   553.9 1762.66   576.2 1770.46
   695.3 1805.62     735 1815.63   774.7 1823.21   814.4 1828.75   864.1 1833.88
   893.8 1835.56   993.1 1838.32  1052.7 1840.89  1062.6    1842  1092.4 1846.75
#Mann= 3 , 0 , 0
       0      .1       0   538.9    .045       0   553.9      .1       0
Bank Sta=538.9,553.9
XS Rating Curve= 0 ,0
Exp/Cntr=0.3,0.1

Type RM Length L Ch R = 1 ,1848.2  ,107.1,100.7,96.5
XS GIS Cut Line= 3
      1983798.52       419438.17     1984337.458      419363.637
     1984878.975      419233.429
#Sta/Elev= 30
       0 1811.83    19.8 1811.66    39.6 1810.93      89  1807.3   108.8    1805
   197.8 1792.59   237.4 1788.55   316.6 1779.47   375.9 1771.13   464.9 1755.34
   536.6 1744.32   544.1  1743.8   551.6 1744.74     554 1745.04     564 1748.27
   583.8 1755.95   603.7 1762.78   663.4 1782.77   703.2 1795.57   752.9 1809.72
   772.8  1814.6   792.7 1818.71   842.4 1826.97   882.2 1831.78     912 1833.88
   961.8 1836.46  1011.5 1838.48  1041.4 1838.62  1051.3  1839.2    1101 1848.43
#Mann= 3 , 0 , 0
       0      .1       0   536.6    .045       0   551.6      .1       0
Bank Sta=536.6,551.6
XS Rating Curve= 0 ,0
Exp/Cntr=0.3,0.1

Type RM Length L Ch R = 1 ,1747.5  ,203.9,199.4,195.2
XS GIS Cut Line= 3
     1984131.438      419499.952     1984339.416      419471.633
     1984567.093      419368.811
#Sta/Elev= 30
       0 1788.81      20 1784.79      30 1782.59      50 1777.59     100 1764.43
   119.9 1759.48   129.9 1757.22   139.9 1755.11   179.9  1746.9   199.9 1742.62
   209.9 1740.28   219.9 1737.64   229.9 1735.41   239.9 1736.67   249.9 1742.39
   259.9 1749.23   269.8  1754.8   279.8 1759.13   289.8 1762.99   299.8 1767.07
   309.8  1770.9   339.8 1782.72   349.8 1786.76   369.8 1793.92   379.8 1796.88
   389.8 1799.55   399.8 1802.01   419.7 1805.88   429.7 1807.51   459.7 1813.08
#Mann= 3 , 0 , 0
       0      .1       0   219.9    .045       0   239.9      .1       0
Bank Sta=219.9,239.9
XS Rating Curve= 0 ,0
Exp/Cntr=0.3,0.1

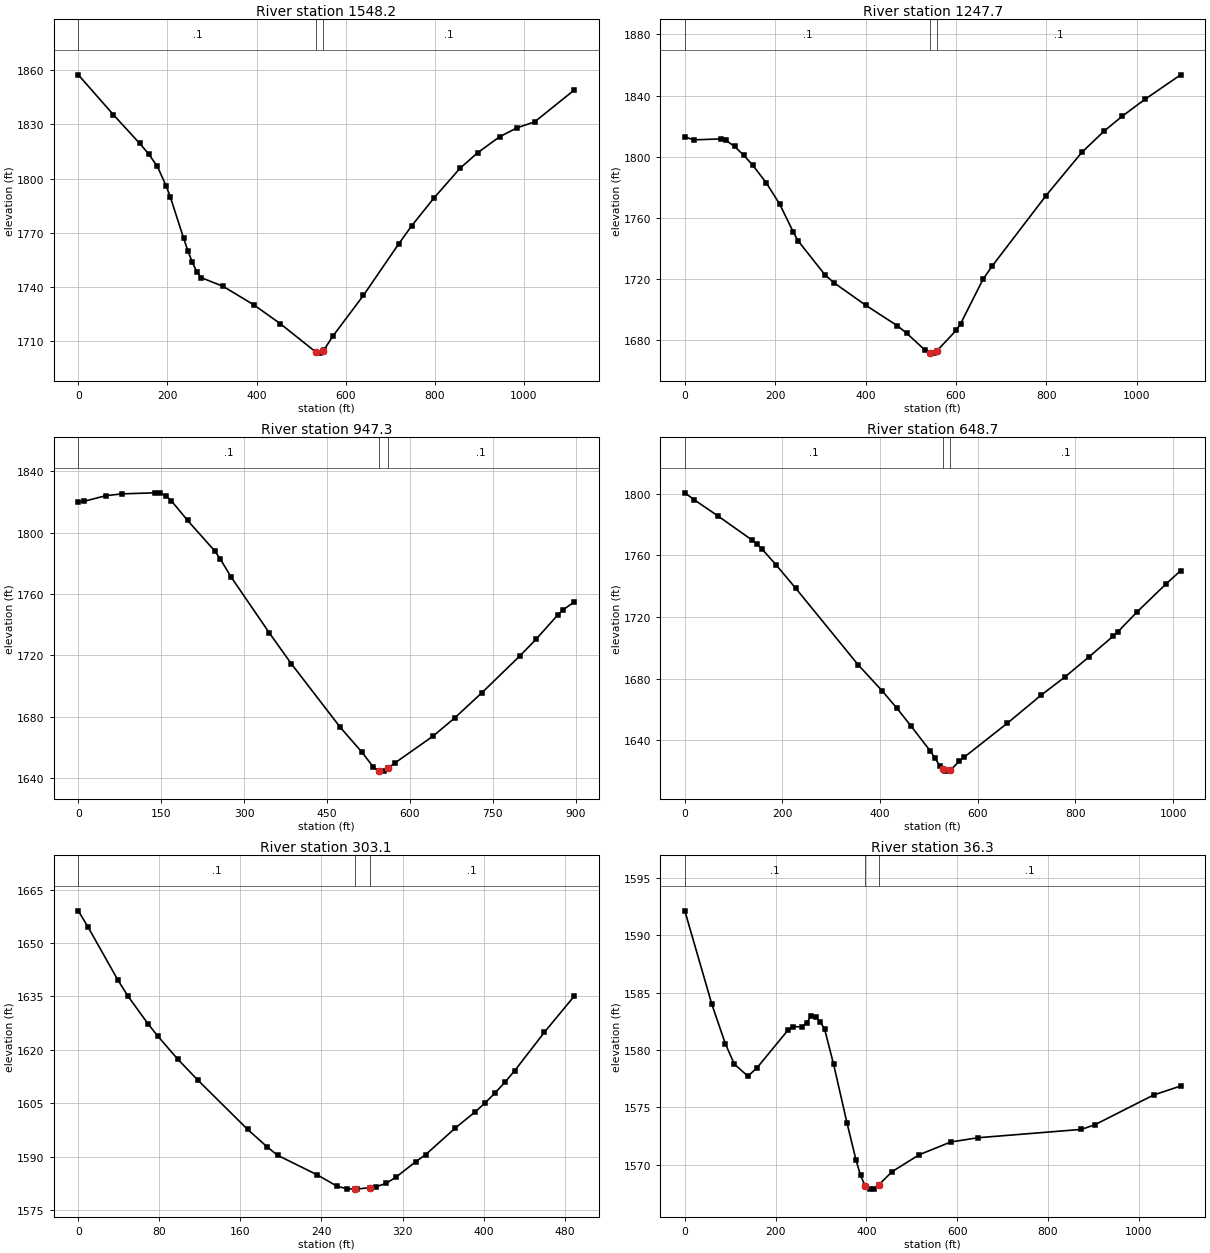
Type RM Length L Ch R = 1 ,1548.2  ,303.8,300.3,293.6
XS GIS Cut Line= 3
     1984004.884      419957.736      1984444.18      419641.377
     1984912.795      419314.636
#Sta/Elev= 30
       0 1857.38    78.7 1835.31   137.8 1819.43   157.5 1813.71   177.2 1806.81
   196.9  1796.1   206.7 1789.66   236.2 1767.07   246.1 1759.93   255.9  1753.7
   265.8 1748.48   275.6 1745.27   324.8 1740.46   393.7 1730.25   452.8 1719.88
   533.9 1703.96   541.4 1703.54   548.9 1704.92   551.2 1705.34   570.9 1712.84
   639.8 1735.49   718.6 1763.82   748.2 1773.97   797.4 1789.11   856.5 1805.71
   895.9 1814.27   945.2 1823.13   984.6  1828.1    1024 1831.39  1112.6 1848.94
#Mann= 3 , 0 , 0
       0      .1       0   533.9    .045       0   548.9      .1       0
Bank Sta=533.9,548.9
XS Rating Curve= 0 ,0
Exp/Cntr=0.3,0.1

Type RM Length L Ch R = 1 ,1247.7  ,292.2,300.6,310.5
XS GIS Cut Line= 3
     1984283.863      420220.509      1984673.71      419831.786
     1985007.867      419399.643
#Sta/Elev= 30
       0 1812.91      20    1811    80.1 1811.63    90.1 1810.85   110.1 1806.68
   130.1 1801.04   150.2 1794.46   180.2 1782.95   210.2  1768.8   240.2 1750.63
   250.2 1745.15   310.3 1722.66   330.3 1717.52   400.4 1702.83   470.5 1689.41
   490.5 1684.65   530.5 1673.78     543 1671.74   550.5 1671.57     558 1673.17
   600.2 1686.41   610.1 1690.85   659.8 1719.88   679.6 1728.36   798.8 1774.46
   878.3 1802.85     928 1816.86   967.7 1826.47  1017.3 1837.39  1096.8 1853.52
#Mann= 3 , 0 , 0
       0      .1       0     543    .045       0     558      .1       0
Bank Sta=543,558
XS Rating Curve= 0 ,0
Exp/Cntr=0.3,0.1

Type RM Length L Ch R = 1 ,947.3   ,311.7,298.3,286
XS GIS Cut Line= 3
     1984333.541      420291.771      1984858.27      420062.302
     1985042.757      419795.575
#Sta/Elev= 30
       0 1819.91     9.9 1820.28    49.4 1823.96      79 1825.18   138.2 1825.85
   148.1 1825.65     158 1824.07   167.9 1820.84   197.5 1807.95   246.9 1787.97
   256.7 1782.83   276.5    1771   345.6 1734.65   385.1 1714.71     474 1673.16
   513.5 1656.87   533.2 1647.57   543.1 1644.72   544.8 1644.74     553 1644.84
   559.8 1646.44   572.7 1650.03   641.5 1667.45   680.8  1679.3     730 1695.71
   798.8 1719.72   828.2 1730.58   867.5 1746.47   877.4 1749.88     897 1754.74
#Mann= 3 , 0 , 0
       0      .1       0   544.8    .045       0   559.8      .1       0
Bank Sta=544.8,559.8
XS Rating Curve= 0 ,0
Exp/Cntr=0.3,0.1

Type RM Length L Ch R = 1 ,648.7   ,345.9,345.4,345.1
XS GIS Cut Line= 3
     1984690.278      420779.486     1985002.748       420289.02
     1985211.684      419908.934
#Sta/Elev= 30
       0  1800.6    19.7 1796.02      69 1785.34     138 1769.88   147.8 1767.26
   157.7 1764.25   187.3  1753.7   226.7 1738.81   354.8 1689.03   404.1 1672.09
   433.7 1661.03   463.3 1649.21   502.7 1633.02   512.6 1628.26   522.4 1623.27
   528.8 1621.13   532.3 1619.96   542.1 1619.97   543.8 1620.49   561.8 1626.32
   571.7 1628.91   660.4 1651.05   729.4 1669.21   778.7 1681.13     828 1694.21
   877.3 1707.58   887.1 1710.51   926.6 1723.44   985.7 1741.54  1015.3 1750.04
#Mann= 3 , 0 , 0
       0      .1       0   528.8    .045       0   543.8      .1       0
Bank Sta=528.8,543.8
XS Rating Curve= 0 ,0
Exp/Cntr=0.3,0.1

Type RM Length L Ch R = 1 ,303.1   ,262.9,266.5,271.1
XS GIS Cut Line= 4
     1985034.941      420614.441     1985228.124      420578.212
     1985305.184      420453.816     1985287.819      420308.384
#Sta/Elev= 30
       0 1659.02     9.8 1654.35    39.3 1639.46    49.1 1635.02    68.8 1627.27
    78.6 1623.77    98.3  1617.3   117.9 1611.49   167.1 1597.63   186.7 1592.64
   196.6 1590.38   235.6  1584.9   255.1 1581.73   264.8 1580.94   272.7 1580.88
   274.6 1580.86   287.7 1581.28   294.1 1581.56   303.9 1582.48   313.6 1584.24
   333.1 1588.57   342.9 1590.57   372.2 1598.05   391.7 1602.56   401.5 1605.07
   411.2 1607.84     421 1610.87   430.8 1614.16     460  1624.9   489.4 1635.04
#Mann= 3 , 0 , 0
       0      .1       0   272.7    .045       0   287.7      .1       0
Bank Sta=272.7,287.7
XS Rating Curve= 0 ,0
Exp/Cntr=0.3,0.1

Type RM Length L Ch R = 1 ,36.3    ,36.1,36.3,35.3
XS GIS Cut Line= 3
     1985069.919      421121.294     1985426.872      420707.812
     1985803.555       420312.43
#Sta/Elev= 30
       0 1592.14    59.6 1583.99    89.4 1580.54   109.2 1578.77     139 1577.72
   158.9 1578.44   228.4 1581.79   238.4 1582.03   258.2 1582.03   268.2 1582.34
   278.1 1582.98     288 1582.92     298 1582.47   307.9 1581.84   327.8 1578.76
   357.5 1573.61   377.4 1570.37   387.3 1569.06   397.3 1568.14   407.2 1567.88
   417.1 1567.87   427.1 1568.24   456.9  1569.4   516.4 1570.87     586 1571.98
   645.5 1572.35   873.9 1573.08   903.7 1573.49  1032.8 1576.08  1092.3 1576.86
#Mann= 3 , 0 , 0
       0      .1       0   397.3    .045       0   427.1      .1       0
Bank Sta=397.3,427.1
XS Rating Curve= 0 ,0
Exp/Cntr=0.3,0.1

Chan Stop Cuts=-1
Use User Specified Reach Order=0
Composite Channel Slope=5